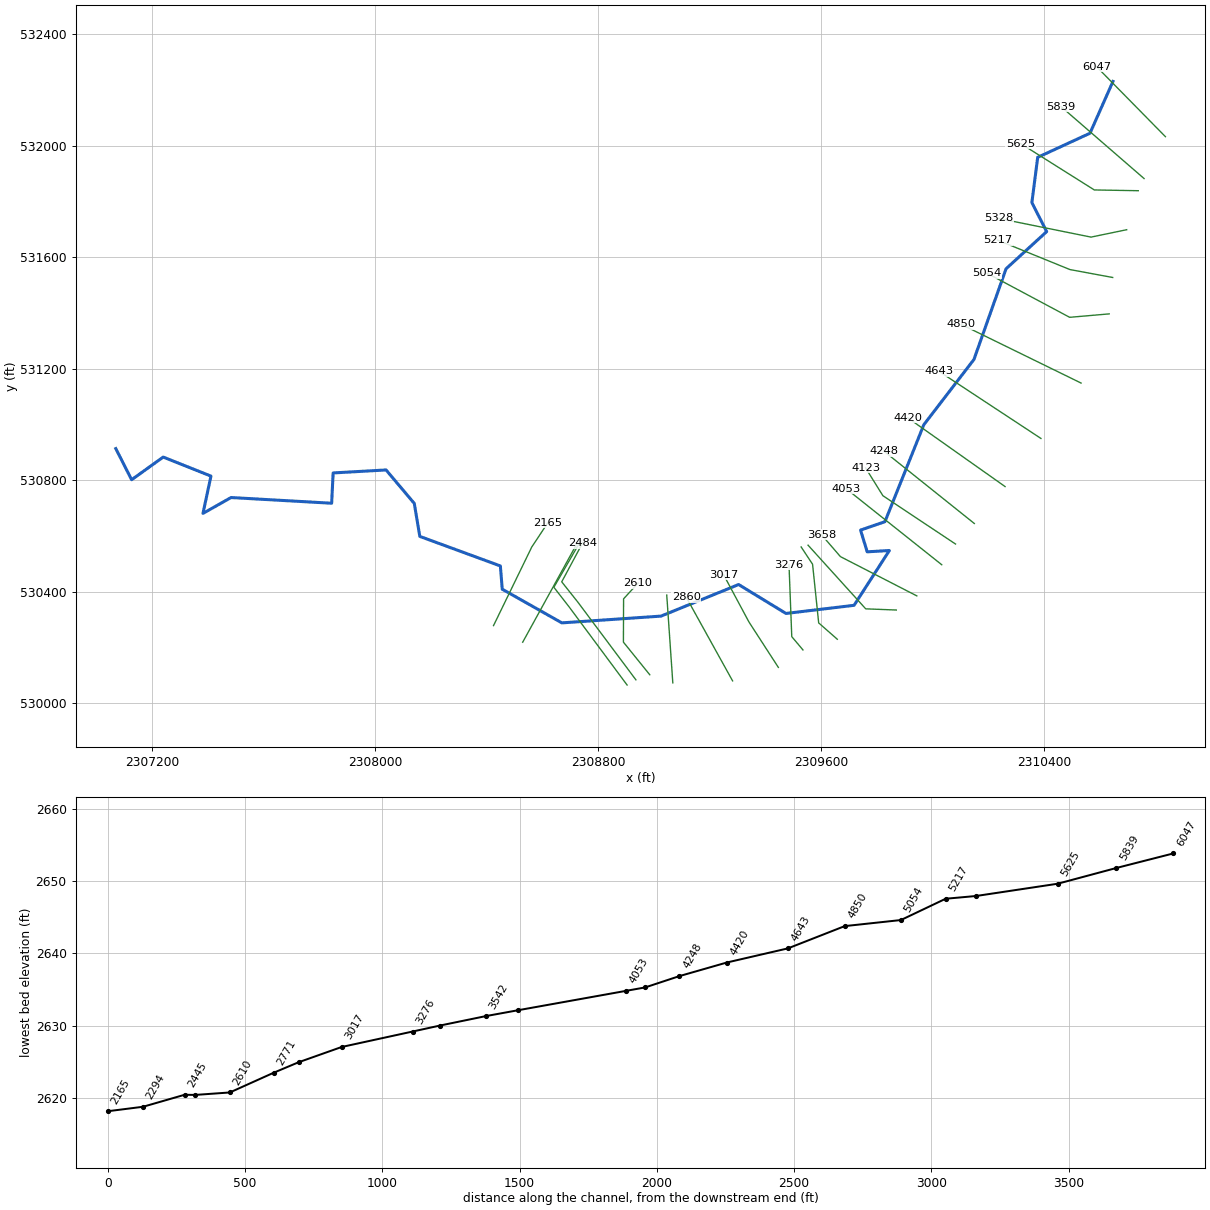
--- DNCNRN.prj (project) ---

Proj Title=DNCNRN
Current Plan=p01
Default Exp/Contr=0,0
English Units
Geom File=g01
Flow File=f01
Plan File=p01
Background Map Layer=Inundation Boundary (01pct Value_0)
Background Map Layer=Inundation Boundary (01pct Value_0)
BEGIN DESCRIPTION:
----------MODEL BY WOOD PLC 2021----------
Stream Name: Duncan Run
Flood Zone: Enhanced Approximate
Pocahontas County, WV
HEC-RAS Version: RAS 6.1
Vertical Datum: NAVD88
Projection: NAD 1983 StatePlane West Virginia S FIPS 4702 (US Feet)
Terrain: 1-meter LIDAR (FEMA Region III 3DEP collected 2016-2018)
Land Use: 2019 NLCD
Hydrologic Method:
WV SIR2010-5033 regression equations
END DESCRIPTION:
DSS Export Rating Curves= 0
DSS Export Rating Curve Sorted= 0
DSS Export Volume Flow Curves= 0
DXF OffsetX= 0
DXF OffsetY= 0
DXF ScaleX= 0
DXF ScaleY= 0

--- DNCNRN.p01 (plan) ---

Plan Title=Floodplain
Program Version=6.10
Short Identifier=Floodplain
Geom File=g01
Flow File=f01
Subcritical Flow
K Sum by GR= 0
Std Step Tol= 0.01
Critical Tol= 0.01
Num of Std Step Trials= 20
Max Error Tol= 0.3
Flow Tol Ratio= 0.001
Split Flow NTrial= 30
Split Flow Tol= 0.02
Split Flow Ratio= 0.02
Log Output Level= 0
Friction Slope Method= 1
Unsteady Friction Slope Method= 2
Unsteady Bridges Friction Slope Method= 1
Parabolic Critical Depth
Global Vel Dist= 0 , 0 , 0
Global Log Level= 0
CheckData=True
Encroach Param=-1 ,0,0, 0
Mapping Interval=1HOUR
Computation Time Step Use Courant=        0
Computation Time Step Use Time Series=    0
Computation Time Step Count To Double=0
Computation Time Step Max Doubling=0
Computation Time Step Max Halving=0
Computation Time Step Residence Courant=0
Run HTab= 0
Run UNet= 0
Run Sediment= 0
Run PostProcess= 0
Run WQNet= 0
Run RASMapper=-1
UNET Theta= 0
UNET Theta Warmup= 0
UNET ZTol= 0
UNET ZSATol= 0
UNET MxIter= 0
UNET Max Iter WO Improvement= 0
UNET MaxInSteps= 0
UNET DtIC= 0
UNET DtMin= 0
UNET MaxCRTS= 0
UNET WFStab= 0
UNET SFStab= 0
UNET WFX= 1
UNET SFX= 1
UNET Gravity=32.174
UNET 1D Methodology=Finite Difference
UNET DSS MLevel= 1
UNET Pardiso=0
UNET DZMax Abort= 0
UNET Use Existing IB Tables= 0
UNET Froude Reduction=False
UNET Froude Limit= 0
UNET Froude Power= 0
UNET D1 Cores= 0
UNET WindReference=Eulerian
UNET WindDragFormulation=Hsu (1988)
UNET D2 Coriolis=0
UNET D2 Cores= 0
UNET D2 Theta= 1
UNET D2 Theta Warmup= 1
UNET D2 Z Tol= 0.01
UNET D2 Volume Tol= 0.01
UNET D2 Max Iterations= 20
UNET D2 Equation= 0
UNET D2 RampUpFraction=0.1
UNET D2 TimeSlices= 1
UNET D2 Turbulence Formulation=Non-Conservative (original)
UNET D2 Eddy Viscosity=0.3
UNET D2 Transverse Eddy Viscosity=0.1
UNET D2 Smagorinsky Mixing=0
UNET D2 BCVolumeCheck=0
UNET D2 Cores=0
UNET D2 SolverType=PARDISO (Direct)
UNET D2 Minimum Iterations= 2147483647
UNET D2 Maximum Iterations= 2147483647
UNET D2 Restart Number= 10
UNET D2 Relaxation Coeff=1.3
UNET D2 SOR Precondition Iterations= 10
UNET D2 ILUT Maximum Fill= 8
UNET D2 ILUT Tolerance=1E-08
UNET D1D2 MaxIter= 0
UNET D1D2 ZTol=0.01
UNET D1D2 QTol=0.1
UNET D1D2 MinQTol=1
Write IC File= 0
Write IC File at Fixed DateTime=0
Write IC File at Sim End=0
Echo Input=False
Echo Parameters=False
Echo Output=False
Write Detailed= 0
HDF Write Warmup=0
HDF Write Time Slices=0
HDF Flush=0
HDF Compression= 1
HDF Chunk Size= 1
HDF Spatial Parts= 1
HDF Use Max Rows=0
HDF Fixed Rows= 1
Calibration Method= 0
Calibration Iterations= 20
Calibration Max Change=0.05
Calibration Tolerance=0.2
Calibration Maximum=1.5
Calibration Minimum=0.5
Calibration Optimization Method= 1
WQ AD Non Conservative
WQ ULTIMATE=-1
WQ Max Comp Step=1HOUR
WQ Output Interval=15MIN
WQ Output Selected Increments= 0
WQ Output face flow=0
WQ Output face velocity=0
WQ Output face area=0
WQ Output face dispersion=0
WQ Output cell volume=0
WQ Output cell surface area=0
WQ Output cell continuity=0
WQ Output cumulative cell continuity=0
WQ Output face conc=0
WQ Output face dconc_dx=0
WQ Output face courant=0
WQ Output face peclet=0
WQ Output face adv mass=0
WQ Output face disp mass=0
WQ Output cell mass=0
WQ Output cell source sink temp=0
WQ Output nsm pathways=0
WQ Output nsm derived pathways=0
WQ Create Restart=0
WQ Fixed Restart=0
WQ System Summary=0
WQ Write To DSS=0
Sorting and Armoring Iterations= 10
XS Update Threshold= 0.02
Bed Roughness Predictor= 0
Hydraulics Update Threshold= 0.02
Energy Slope Method= 1
Volume Change Method= 1
Sediment Retention Method= 0
Sediment TS Multiplier= 1
Warm Up Method= 0
XS Weighting Method= 0
Number of US Weighted Cross Sections= 1
Number of DS Weighted Cross Sections= 1
Upstream XS Weight=0
Main XS Weight=1
Downstream XS Weight=0
Number of DS XS's Weighted with US Boundary= 1
Upstream Boundary Weight= 1
Weight of XSs Associated with US Boundary= 0
Number of US XS's Weighted with DS Boundary= 1
Downstream Boundary Weight= 0.5
Weight of XSs Associated with DS Boundary= 0.5
Percentile Method= 0
Sediment Output Level= 3
Mass or Volume Output= 0
Output Increment Type= 1
Profile and TS Output Increment= 1
Transport Output Increment 1
XS Output Flag= 0
XS Output Increment= 10
Read HDF5 Sediment Hotstart= 0
Sediment Hotstart Type= 0
Write Gradation File= 0
Read Gradation Hotstart= 0
Write HDF5 File= 1
Write Binary Output= 1
Write DSS Sediment File= 0
DSS Sediment Output Type= 1
SV Curve= 0
Specific Gage Flag= 0
Subcell Erosion Methods= 0
Subcell Deposition Methods= 0
Advection Scheme= 1
Matrix Solver= 0
Implicit Weighting Factor= 1
Maximum Outer Loop Convergence Iterations= 5
Convergence Maximum Absolute= 0.001
Convergence RMSE= 0.0001
Grain Fractions Max Abs Error= 0.001
Max Subgrid Regions= 1
Max Subgrid Length Scale= 3.402823E+38
Initial Layer Thickness= 3.402823E+38
Min Layer Thickness= 3.402823E+38
Max Layer Thickness= 3.402823E+38
Number of Layers= 5

--- DNCNRN.f01 (steady flow) ---

Flow Title=Flow
Program Version=6.10
Number of Profiles= 6
Profile Names=01pct,10pct,04pct,02pct,0_2pct,01plus
River Rch & RM=DNCNRN,Main            ,6047
     718     383     507     609     999    1060
River Rch & RM=DNCNRN,Main            ,2294
     825     442     584     701    1140    1220
Boundary for River Rch & Prof#=DNCNRN,Main            , 1
Up Type= 0
Dn Type= 3
Dn Slope=0.0056
Boundary for River Rch & Prof#=DNCNRN,Main            , 2
Up Type= 0
Dn Type= 3
Dn Slope=0.0056
Boundary for River Rch & Prof#=DNCNRN,Main            , 3
Up Type= 0
Dn Type= 3
Dn Slope=0.0056
Boundary for River Rch & Prof#=DNCNRN,Main            , 4
Up Type= 0
Dn Type= 3
Dn Slope=0.0056
Boundary for River Rch & Prof#=DNCNRN,Main            , 5
Up Type= 0
Dn Type= 3
Dn Slope=0.0056
Boundary for River Rch & Prof#=DNCNRN,Main            , 6
Up Type= 0
Dn Type= 3
Dn Slope=0.0056
DSS Import GetInterval= 0
DSS Import GetPeak= 0
DSS Import FillOption= 0

--- DNCNRN.g01 (geometry) ---

Geom Title=Geometry
Program Version=6.10

River Reach=DNCNRN          ,Main
Reach XY= 30
2310645.76100002532230.9030000122310563.37600002532045.047999993
2310375.75800002531958.6050000042310354.83800001531796.062000021
2310407.97900005531692.0650000132310262.20200002531558.722000018
2310147.11700004531233.538000003      2309967.19530999.257000014
2309827.66000001530651.409999996     2309740.186530621.256999999
2309764.12600003      530543.2722309843.64000003530548.047000006
     2309716.964530351.382000014     2309472.616530322.229000017
2309302.70200001530425.9790000172309024.47200002530312.686000004
2308668.58599998530288.4440000062308454.75700003530409.231000006
2308448.03300002530492.6460000132308159.05000003530598.638000011
2308139.12300003530717.078951091     2308037.928530837.020999998
2307848.09500001530826.3260000052307842.72000003530717.649000004
2307481.82900004530738.0789999962307381.11000001530681.167000011
2307409.71100003530814.9250000122307238.59999999530883.254000008
2307125.16500001530801.9749999942307068.30703358530913.615071982

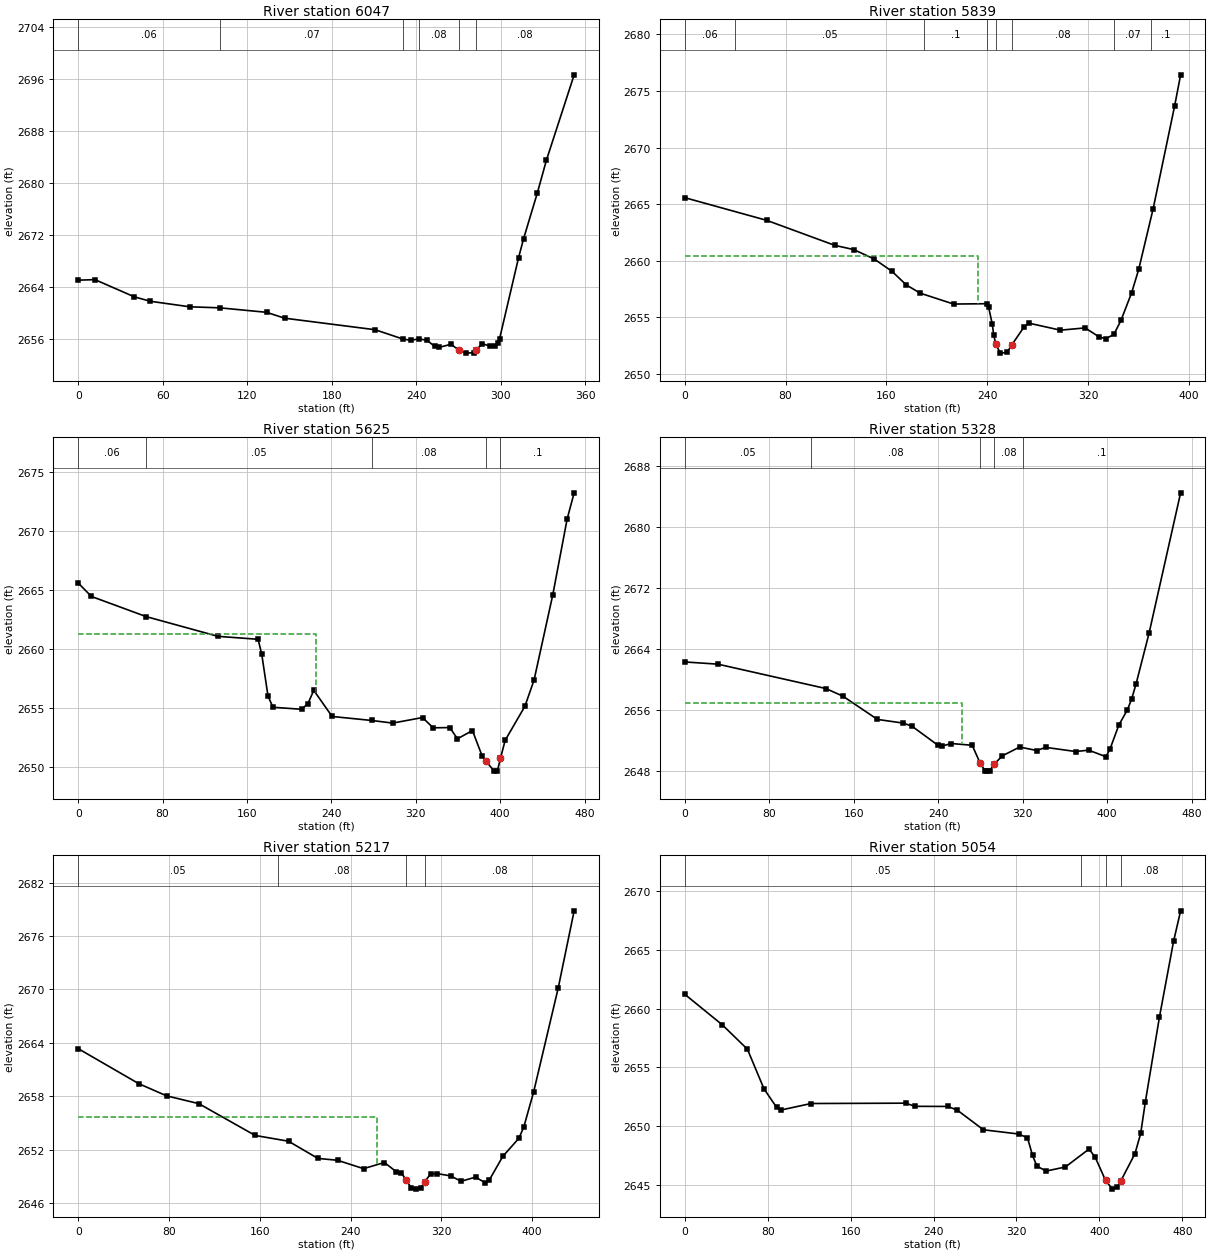
Type RM Length L Ch R = 1 ,6047    ,208.3,208.1,209.4
XS GIS Cut Line= 2
2310833.97265101532032.6979740622310586.98157398532283.834095194
#Sta/Elev= 30
       0 2665.07    11.9 2665.15    39.9  2662.5    51.2 2661.82    79.2 2660.97
   100.6 2660.81   133.8 2660.12   146.5 2659.22   210.9 2657.44   230.7    2656
   236.4 2655.82   241.9 2656.03   247.7 2655.82   253.1 2654.88   256.2 2654.72
   264.7  2655.2   270.7 2654.25   275.6 2653.84   281.2 2653.92  282.68 2654.28
   286.8 2655.31   292.4 2654.91   295.8 2654.99     298 2655.42   299.2 2656.02
   312.7 2668.51   316.3 2671.46   326.1 2678.52   332.5 2683.53   352.2 2696.67
#Mann= 6 ,-1,0
       0     .06       0   100.6     .07       0   230.7      .1       0
   241.9     .08       0   270.7    .045       0  282.68     .08       0
Bank Sta=270.7,282.68
XS Rating Curve= 0 ,0
Exp/Cntr(USF)=0,0
Exp/Cntr=0.3,0.1

Type RM Length L Ch R = 1 ,5839    ,211.8,213.6,215.8
XS GIS Cut Line= 2
2310757.35656297 531882.506343352310460.14685995532139.961882269
#Sta/Elev= 30
       0 2665.57    65.1 2663.56     119 2661.35   133.9 2660.98   150.2 2660.15
   164.4 2659.05   175.7 2657.85   186.8 2657.12   213.2 2656.16   239.7 2656.19
   240.9 2655.92   243.8 2654.42     245 2653.46   246.6 2652.61   250.3 2651.82
   255.6 2651.88   259.32652.545   269.3 2654.17   272.9 2654.47   297.9 2653.85
   317.5 2654.05   328.8 2653.24     334  2653.1   340.3 2653.48   345.9 2654.71
   354.4 2657.17     360 2659.24   371.4 2664.58   388.4 2673.65   393.2 2676.43
#Mann= 8 ,-1,0
       0     .06       0      40     .05       0     190      .1       0
     240     .08       0   246.6    .045       0   259.3     .08       0
     340     .07       0     370      .1       0
#XS Ineff= 2 , 0
          232.53 2660.43
Permanent Ineff=
       F       F
Bank Sta=246.6,259.3
XS Rating Curve= 0 ,0
Exp/Cntr(USF)=0,0
Exp/Cntr=0.3,0.1

Type RM Length L Ch R = 1 ,5625    ,293.7,297.4,303.1
XS GIS Cut Line= 3
2310736.64871398531838.8468914332310578.94630911 531841.55368852
2310314.64716372532007.996171472
#Sta/Elev= 30
       0 2665.58    12.5 2664.44    64.5 2662.73   132.5 2661.06   170.5 2660.81
     174 2659.53   179.9    2656   184.6 2655.05   211.7 2654.88   217.7 2655.36
   223.3 2656.48   240.7 2654.27   278.4 2653.93   298.1 2653.71   326.4 2654.18
   336.4 2653.31   352.2 2653.33   359.5 2652.38   373.7 2653.08   382.8 2650.94
  386.66 2650.46   394.4 2649.64   397.4 2649.67   400.2 2650.71   404.7 2652.25
   423.4 2655.13   432.1 2657.36   449.8 2664.56   463.5 2671.02   470.1 2673.22
#Mann= 5 ,-1,0
       0     .06       0    64.5     .05       0   278.4     .08       0
  386.66    .045       0   400.2      .1       0
#XS Ineff= 2 , 0
          225.44 2661.22
Permanent Ineff=
       T       F
Bank Sta=386.66,400.2
XS Rating Curve= 0 ,0
Exp/Cntr(USF)=0,0
Exp/Cntr=0.3,0.1

Type RM Length L Ch R = 1 ,5328    ,112.9,110.7,109.7
XS GIS Cut Line= 3
2310694.88573367531698.8799663272310567.10449193531672.377190261
 2310234.8732634531739.580658141
#Sta/Elev= 30
       0 2662.26    31.4 2661.97   133.7 2658.77   149.8 2657.77   182.5 2654.72
   206.9 2654.24   215.1 2653.84   239.6 2651.35   243.7 2651.23   252.5 2651.56
   272.2 2651.33   279.6 2649.02   284.5 2647.96   286.4 2647.94   288.6 2647.95
   292.6 2648.81   300.8 2649.95   317.1  2651.1   333.5 2650.64   341.6 2651.06
   370.2 2650.51   382.4 2650.69   398.8 2649.83   402.8 2650.89     411 2653.98
   419.2    2656   423.2 2657.44   427.3 2659.36   439.6 2666.02   469.5 2684.44
#Mann= 5 ,-1,0
       0     .05       0     120     .08       0   279.6    .045       0
   292.6     .08       0   320.5      .1       0
#XS Ineff= 2 , 0
          262.48 2656.89
Permanent Ineff=
       F       F
Bank Sta=279.6,292.6
XS Rating Curve= 0 ,0
Exp/Cntr(USF)=0,0
Exp/Cntr=0.3,0.1

Type RM Length L Ch R = 1 ,5217    ,163.1,163,160.1
XS GIS Cut Line= 3
2310644.71976469531527.558449619 2310491.3822746531555.954281118
2310231.08715253531661.965385378
#Sta/Elev= 30
       0 2663.34    53.3 2659.41    77.8 2658.04   106.3 2657.16   155.9 2653.59
   185.3 2652.94   211.2 2651.01   228.5  2650.8   251.4 2649.86   269.8 2650.55
   280.3 2649.51   284.7  2649.4     289 2648.57   293.3 2647.74   297.5 2647.56
   301.9 2647.69   305.3 2648.39   310.6 2649.28   315.9 2649.31   328.1 2649.05
   337.4 2648.44   350.1 2648.91   358.8 2648.26   362.4 2648.62   374.2 2651.25
   388.3 2653.27   392.6 2654.53   401.3 2658.48   422.9 2670.12     437 2678.82
#Mann= 4 ,-1,0
       0     .05       0  175.94     .08       0     289    .045       0
   305.3     .08       0
#XS Ineff= 2 , 0
          263.29 2655.61
Permanent Ineff=
       F       F
Bank Sta=289,305.3
XS Rating Curve= 0 ,0
Exp/Cntr(USF)=0,0
Exp/Cntr=0.3,0.1

Type RM Length L Ch R = 1 ,5054    ,203.9,204.7,204.9
XS GIS Cut Line= 3
2310632.41490438531396.9376247272310490.43574688531384.632764411
2310194.17257158531542.702893085
#Sta/Elev= 30
       0 2661.23    36.4 2658.61    60.5 2656.54    76.5 2653.16    88.6 2651.59
    92.6 2651.35   121.9 2651.91   213.1 2651.94   222.1 2651.67   253.9 2651.66
     263 2651.34   288.1 2649.67   322.1 2649.31   330.6 2648.99   335.5 2647.48
   339.7 2646.57   348.6 2646.15   367.2  2646.5     390 2648.03   395.9 2647.33
   405.92645.355   412.6 2644.61   417.1 2644.77   420.62645.306   434.3 2647.64
   439.8 2649.36   444.3 2652.06   457.9 2659.29   471.5 2665.74   478.3 2668.34
#Mann= 4 ,-1,0
       0     .05       0  382.51     .08       0   405.9    .045       0
   420.6     .08       0
Bank Sta=405.9,420.6
XS Rating Curve= 0 ,0
Exp/Cntr(USF)=0,0
Exp/Cntr=0.3,0.1

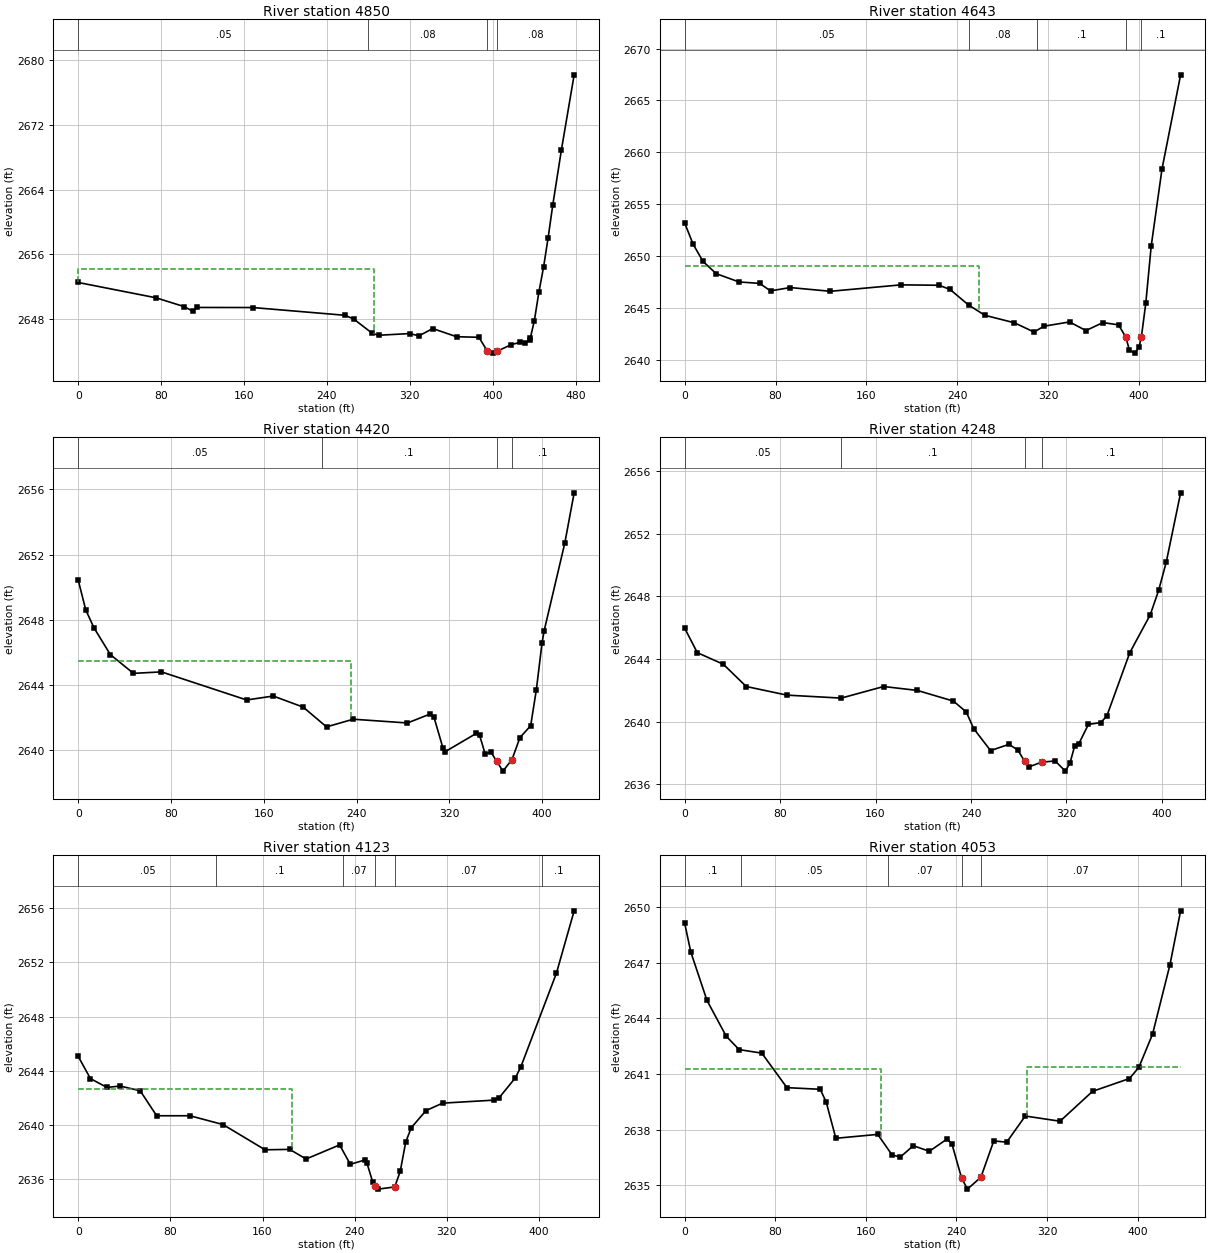
Type RM Length L Ch R = 1 ,4850    ,207.8,206.5,205.6
XS GIS Cut Line= 2
2310531.45407597531148.741977419 2310101.6863473    531359.08147
#Sta/Elev= 30
       0 2652.51    74.9 2650.62   102.1 2649.53   110.4 2648.97     115 2649.42
   168.4 2649.41   257.5 2648.45   265.9 2647.98   283.8 2646.21   289.8 2645.98
   319.8 2646.19   328.7 2645.91   342.1 2646.81     365  2645.8   386.6 2645.73
   394.5 2644.07     400 2643.77   404.5 2644.02   417.8 2644.82   426.7 2645.12
   431.2 2644.99   435.6 2645.39   436.3 2645.69   440.1 2647.78   444.5 2651.34
     449 2654.42   453.4 2658.05   457.9 2662.12   466.2 2668.91   478.5  2678.2
#Mann= 4 ,-1,0
       0     .05       0     280     .08       0   394.5    .045       0
   404.5     .08       0
#XS Ineff= 2 , 0
          285.71 2654.19
Permanent Ineff=
       F       F
Bank Sta=394.5,404.5
XS Rating Curve= 0 ,0
Exp/Cntr(USF)=0,0
Exp/Cntr=0.3,0.1

Type RM Length L Ch R = 1 ,4643    ,222.4,222.7,219.8
XS GIS Cut Line= 2
 2310387.3325718530950.088012204 2310022.4844396531190.290519164
#Sta/Elev= 30
       0 2653.21     7.4 2651.18    16.1 2649.52    27.7 2648.34    47.8 2647.54
      66  2647.4    75.6 2646.68    92.9    2647   128.3 2646.64   190.6 2647.26
   224.1 2647.22   233.7 2646.82     250 2645.32   264.4 2644.33   290.4 2643.61
   307.7 2642.72   316.4 2643.28     339 2643.69   353.4 2642.86   368.4 2643.63
   382.1 2643.41   388.6 2642.22   391.7 2640.97   396.5 2640.69   400.1 2641.24
  402.24 2642.24   406.1 2645.47   410.9    2651   420.4 2658.41   436.8 2667.47
#Mann= 5 ,-1,0
       0     .05       0     250     .08       0     310      .1       0
   388.6    .045       0  402.24      .1       0
#XS Ineff= 2 , 0
          259.14 2649.03
Permanent Ineff=
       F       F
Bank Sta=388.6,402.24
XS Rating Curve= 0 ,0
Exp/Cntr(USF)=0,0
Exp/Cntr=0.3,0.1

Type RM Length L Ch R = 1 ,4420    ,174.6,172.6,172.5
XS GIS Cut Line= 2
2310258.79177078530777.4018855792309909.52434174531024.096352186
#Sta/Elev= 30
       0 2650.43     6.5 2648.61    13.5 2647.52    27.7 2645.87    47.6 2644.72
    71.8 2644.81   145.2 2643.09   168.2 2643.33     194 2642.65   214.1 2641.44
   237.1 2641.91   283.9 2641.68   303.1 2642.22   306.8 2642.02   314.5 2640.14
   316.6 2639.93   343.2 2641.04     346 2640.94   350.9 2639.78   355.8 2639.89
   360.7 2639.35   366.2 2638.73     374 2639.44   380.9 2640.79   390.1 2641.51
     395 2643.71   399.9 2646.58   401.7 2647.32   419.5 2652.69   427.6 2655.78
#Mann= 4 ,-1,0
       0     .05       0     210      .1       0   360.7    .045       0
     374      .1       0
#XS Ineff= 2 , 0
          235.05  2645.5
Permanent Ineff=
       F       F
Bank Sta=360.7,374
XS Rating Curve= 0 ,0
Exp/Cntr(USF)=0,0
Exp/Cntr=0.3,0.1

Type RM Length L Ch R = 1 ,4248    ,124.2,124.9,126.1
XS GIS Cut Line= 2
2310148.42845677530644.9659087692309823.83047439530904.644294671
#Sta/Elev= 30
       0 2645.97    10.6 2644.41    32.4 2643.67    51.6 2642.25    85.7  2641.7
   131.2 2641.51   166.8 2642.25     195    2642   225.2 2641.32     236 2640.63
   242.2 2639.57   256.4 2638.16   271.8 2638.56   279.2  2638.2   284.9 2637.49
   288.5 2637.12   299.1 2637.42   310.5  2637.5   319.1 2636.85     323 2637.37
   326.9 2638.46   330.4  2638.6   338.4 2639.83   348.7 2639.95   353.8 2640.36
   373.1 2644.41   390.2 2646.82   397.3 2648.39   403.7  2650.2   415.7 2654.61
#Mann= 4 ,-1,0
       0     .05       0   131.2      .1       0   284.9    .045       0
   299.1      .1       0
Bank Sta=284.9,299.1
XS Rating Curve= 0 ,0
Exp/Cntr(USF)=0,0
Exp/Cntr=0.3,0.1

Type RM Length L Ch R = 1 ,4123    ,71.7,70.2,69.5
XS GIS Cut Line= 3
 2310080.8529253530571.2982429342309820.31691812530744.679802276
2309758.22677324530844.531930095
#Sta/Elev= 30
       0 2645.07    10.6 2643.43    24.9 2642.78    36.5 2642.88    53.8 2642.53
    68.1 2640.69      97 2640.69   125.7 2640.04   162.2 2638.18   183.6 2638.21
   197.8  2637.5   226.9 2638.54   236.2 2637.11   248.9 2637.43   250.7 2637.18
   255.7 2635.79   257.92635.482   260.3 2635.28   274.7 2635.44   279.5 2636.58
   284.3 2638.75   289.1 2639.81   301.9 2641.07   316.3 2641.62   360.6 2641.84
   365.4 2642.02   379.5 2643.49   384.2 2644.29   415.1  2651.2   430.5  2655.8
#Mann= 6 ,-1,0
       0     .05       0     120      .1       0     230     .07       0
   257.9    .045       0   274.7     .07       0  402.95      .1       0
#XS Ineff= 2 , 0
          185.99 2642.67
Permanent Ineff=
       F       F
Bank Sta=257.9,274.7
XS Rating Curve= 0 ,0
Exp/Cntr(USF)=0,0
Exp/Cntr=0.3,0.1

Type RM Length L Ch R = 1 ,4053    ,381.7,394.4,386.7
XS GIS Cut Line= 2
2310031.57318311530496.9492288042309688.79771372530769.611534002
#Sta/Elev= 30
       0 2649.13     5.4 2647.58    19.7 2644.97    36.7 2643.04    48.1 2642.32
    68.1 2642.13    90.3 2640.27   119.7 2640.18     125 2639.49   133.5 2637.54
   170.5 2637.75   183.2 2636.64   190.5 2636.53   201.9 2637.14   216.1 2636.84
   231.7  2637.5     236 2637.24   244.5 2635.41   249.7  2634.8   261.6 2635.44
     273  2637.4   284.4 2637.33   300.8 2638.74   331.5 2638.46   360.2 2640.07
   392.8 2640.76   401.1 2641.36   413.2 2643.15   428.6  2646.9     438  2649.8
#Mann= 6 ,-1,0
       0      .1       0      50     .05       0     180     .07       0
   244.5    .045       0   261.6     .07       0     438      .1       0
#XS Ineff= 2 , 0
          173.11 2641.29  302.74         2641.38
Permanent Ineff=
       F       F
Bank Sta=244.5,261.6
XS Rating Curve= 0 ,0
Exp/Cntr(USF)=0,0
Exp/Cntr=0.3,0.1

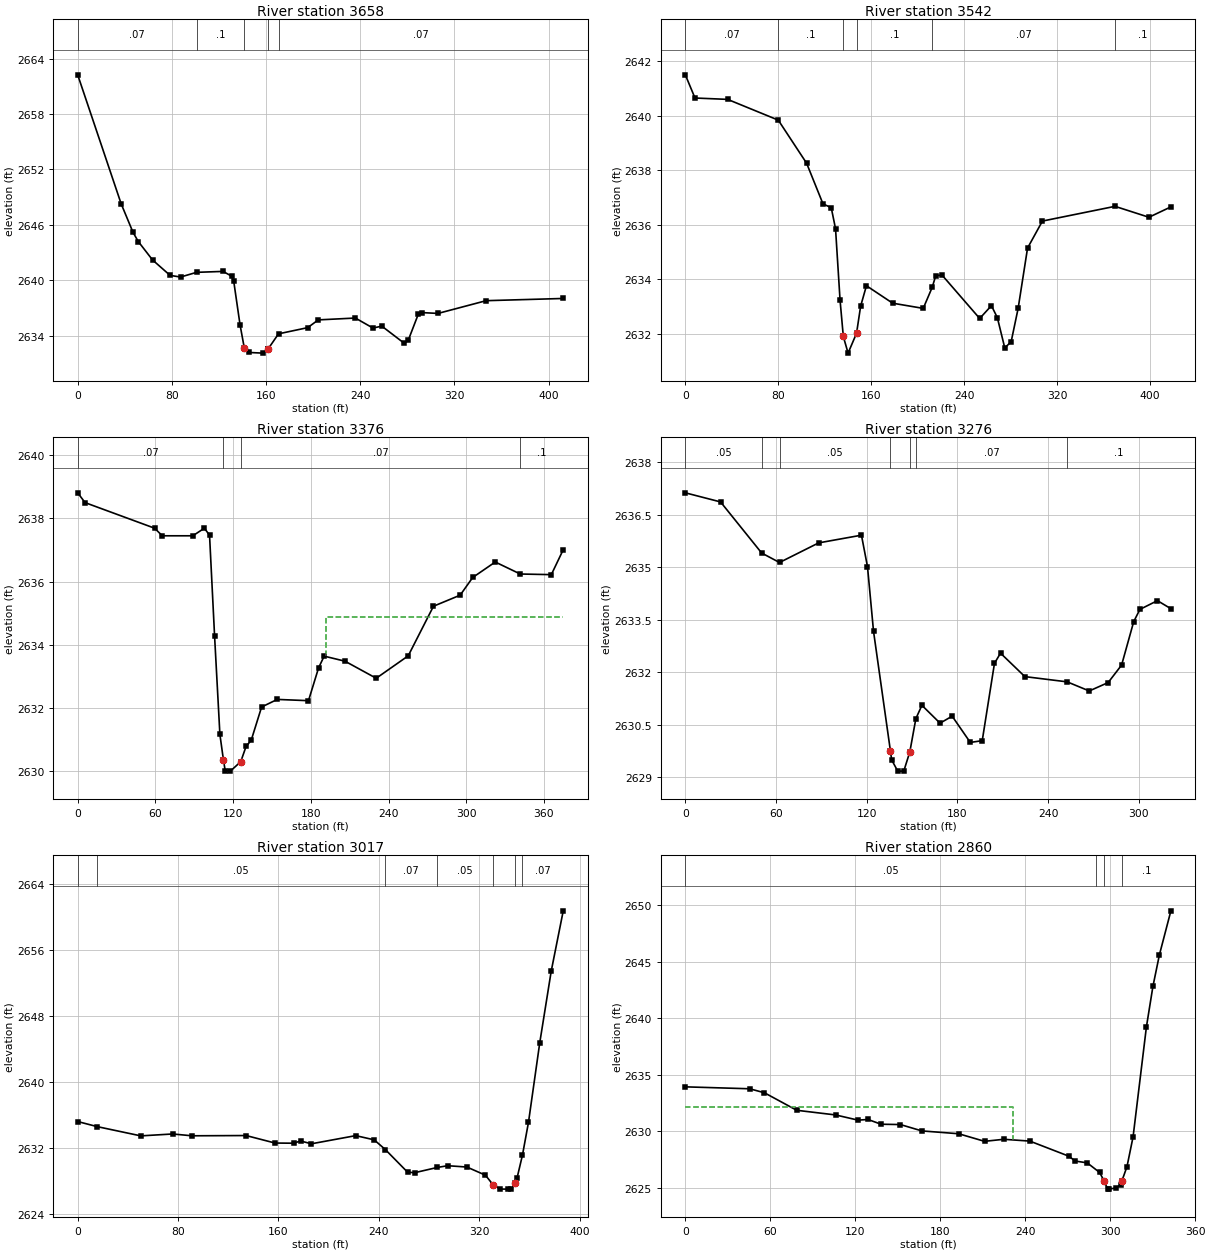
Type RM Length L Ch R = 1 ,3658    ,121.4,116.6,112.2
XS GIS Cut Line= 3
2309941.98413997530385.2875228662309668.08316888530526.048788729
2309599.66959972530605.092292613
#Sta/Elev= 30
       0 2662.25    36.9 2648.29      47 2645.19    51.5 2644.19    63.6  2642.2
    78.5 2640.53    87.4 2640.35     101 2640.86   123.5 2640.96     131 2640.43
   132.5 2639.95   137.9  2635.2   141.5 2632.69   145.9 2632.18   157.3 2632.11
   161.7 2632.54   161.7 2632.55   170.6  2634.2   195.4 2634.87   204.4 2635.71
   235.9 2635.91   250.8 2634.83   258.4 2635.03   277.5 2633.17   280.9 2633.53
   289.4 2636.34   292.4  2636.5   306.1 2636.41     347 2637.79   412.5 2638.03
#Mann= 5 ,-1,0
       0     .07       0     101      .1       0   141.5    .045       0
   161.7      .1       0   170.6     .07       0
Bank Sta=141.5,161.7
XS Rating Curve= 0 ,0
Exp/Cntr(USF)=0,0
Exp/Cntr=0.3,0.1

Type RM Length L Ch R = 1 ,3542    ,172.8,166,159.7
XS GIS Cut Line= 3
2309868.50198789530334.5349693952309758.77175367530338.732300759
2309551.90327934530567.187050677
#Sta/Elev= 30
       0  2641.5     8.3 2640.65    36.4  2640.6      80 2639.84   104.4 2638.26
   118.5 2636.77   125.6 2636.63   129.3 2635.86   133.2 2633.24     136 2631.91
   140.1  2631.3   147.4 2632.03   150.9 2633.02   155.9 2633.77   178.5 2633.13
   204.8 2632.94   212.5 2633.71   215.6 2634.14     221 2634.16   253.4 2632.57
   263.5 2633.04   268.6  2632.6     275 2631.49   280.5 2631.72   286.5 2632.94
   294.6 2635.15   307.4 2636.14   369.9 2636.68   399.1 2636.28     418 2636.66
#Mann= 6 ,-1,0
       0     .07       0      80      .1       0     136    .045       0
   147.4      .1       0   212.5     .07       0   369.9      .1       0
Bank Sta=136,147.4
XS Rating Curve= 0 ,0
Exp/Cntr(USF)=0,0
Exp/Cntr=0.3,0.1

Type RM Length L Ch R = 1 ,3376    ,100.4,100,99.3
XS GIS Cut Line= 4
2309656.81022555530229.7022620372309589.99909751530288.339983761
2309568.09298603530498.8305113312309527.04145217530560.826891337
#Sta/Elev= 30
       0 2638.81     5.7  2638.5    59.4 2637.69    65.3 2637.45    88.9 2637.45
    97.8 2637.69   101.8 2637.47   105.7 2634.27   109.8 2631.16  112.522630.358
   113.9 2630.01   117.9    2630   125.9  2630.3     130 2630.78     134 2630.98
     142 2632.03   154.1 2632.27   178.2 2632.23     186 2633.27   190.3 2633.64
   206.4 2633.48   230.5 2632.94   255.2 2633.65   274.7 2635.22   295.3 2635.57
     305 2636.13   322.4 2636.62   341.7 2636.24   365.7 2636.22   374.9 2637.01
#Mann= 4 ,-1,0
       0     .07       0  112.52    .045       0   125.9     .07       0
   341.7      .1       0
#XS Ineff= 2 , 0
                          191.39         2634.87
Permanent Ineff=
       F       F
Bank Sta=112.52,125.9
XS Rating Curve= 0 ,0
Exp/Cntr(USF)=0,0
Exp/Cntr=0.3,0.1

Type RM Length L Ch R = 1 ,3276    ,251.5,258.4,266.6
XS GIS Cut Line= 3
2309533.57752986530191.3642050382309493.46907341530239.061103173
2309483.50092889530497.723385442
#Sta/Elev= 30
       0 2637.12    23.3 2636.86    50.5  2635.4    62.3 2635.13    88.2 2635.69
   116.5 2635.91   120.5 2635.01   124.5 2633.16  135.672629.745   136.5 2629.49
   140.5 2629.17   144.5 2629.17   148.5 2629.72   152.5 2630.67   156.5 2631.05
   168.5 2630.54   176.5 2630.74   188.5 2629.99   196.4 2630.04   204.5 2632.25
   208.5 2632.54   224.6 2631.87   252.6 2631.72   267.2 2631.46   279.7  2631.7
   288.6  2632.2   296.6 2633.44   300.7 2633.79   312.3 2634.04   321.2 2633.81
#Mann= 7 ,-1,0
       0     .05       0    50.5     .07       0    62.3     .05       0
  135.67    .045       0   148.5     .05       0   152.5     .07       0
   252.6      .1       0
Bank Sta=135.67,148.5
XS Rating Curve= 0 ,0
Exp/Cntr(USF)=0,0
Exp/Cntr=0.3,0.1

Type RM Length L Ch R = 1 ,3017    ,156.8,157.3,157.4
XS GIS Cut Line= 3
2309445.32383959530128.7228081642309339.79241901530291.668429739
2309248.61024898530461.673778623
#Sta/Elev= 30
       0 2635.23    15.6 2634.61    50.3 2633.49    75.7 2633.72    91.1  2633.5
   134.2 2633.53   157.3 2632.62   172.1  2632.6   177.6 2632.87   186.3 2632.53
   221.6 2633.52   236.3 2633.01   245.2 2631.83   262.9 2629.09   268.5 2629.02
   286.6 2629.66   294.9 2629.87   310.2 2629.71     325 2628.72   330.9 2627.59
   336.6 2627.04   342.7 2627.03   345.7 2627.07   348.6  2627.8   350.2 2628.39
   354.5 2631.16   359.3 2635.14   368.3 2644.81   377.4 2653.46     387 2660.79
#Mann= 7 ,-1,0
       0      .1       0    15.6     .05       0   245.2     .07       0
   286.6     .05       0   330.9    .045       0   348.6     .05       0
   354.5     .07       0
Bank Sta=330.9,348.6
XS Rating Curve= 0 ,0
Exp/Cntr(USF)=0,0
Exp/Cntr=0.3,0.1

Type RM Length L Ch R = 1 ,2860    ,95.4,89.4,85.1
XS GIS Cut Line= 2
2309281.11536109530080.3373552412309114.92119411530380.265890959
#Sta/Elev= 30
       0 2633.94    45.4 2633.77    55.8 2633.42    78.7 2631.87   106.1 2631.46
     122    2631     129 2631.06   138.2 2630.64   151.9 2630.61     167 2630.05
     193  2629.8   211.3 2629.13   224.9 2629.31   243.3 2629.15   270.8 2627.82
   275.3 2627.39   283.8 2627.23   292.6 2626.38   295.6 2625.66   298.2 2624.93
     299 2624.91   304.4 2625.02   307.4 2625.31  308.312625.635   311.9  2626.9
   316.2 2629.53   325.6 2639.22   330.2  2642.8   334.8  2645.6   342.9 2649.48
#Mann= 4 ,-1,0
       0     .05       0     290      .1       0   295.6    .045       0
  308.31      .1       0
#XS Ineff= 2 , 0
          231.49 2632.14
Permanent Ineff=
       F       F
Bank Sta=295.6,308.31
XS Rating Curve= 0 ,0
Exp/Cntr(USF)=0,0
Exp/Cntr=0.3,0.1

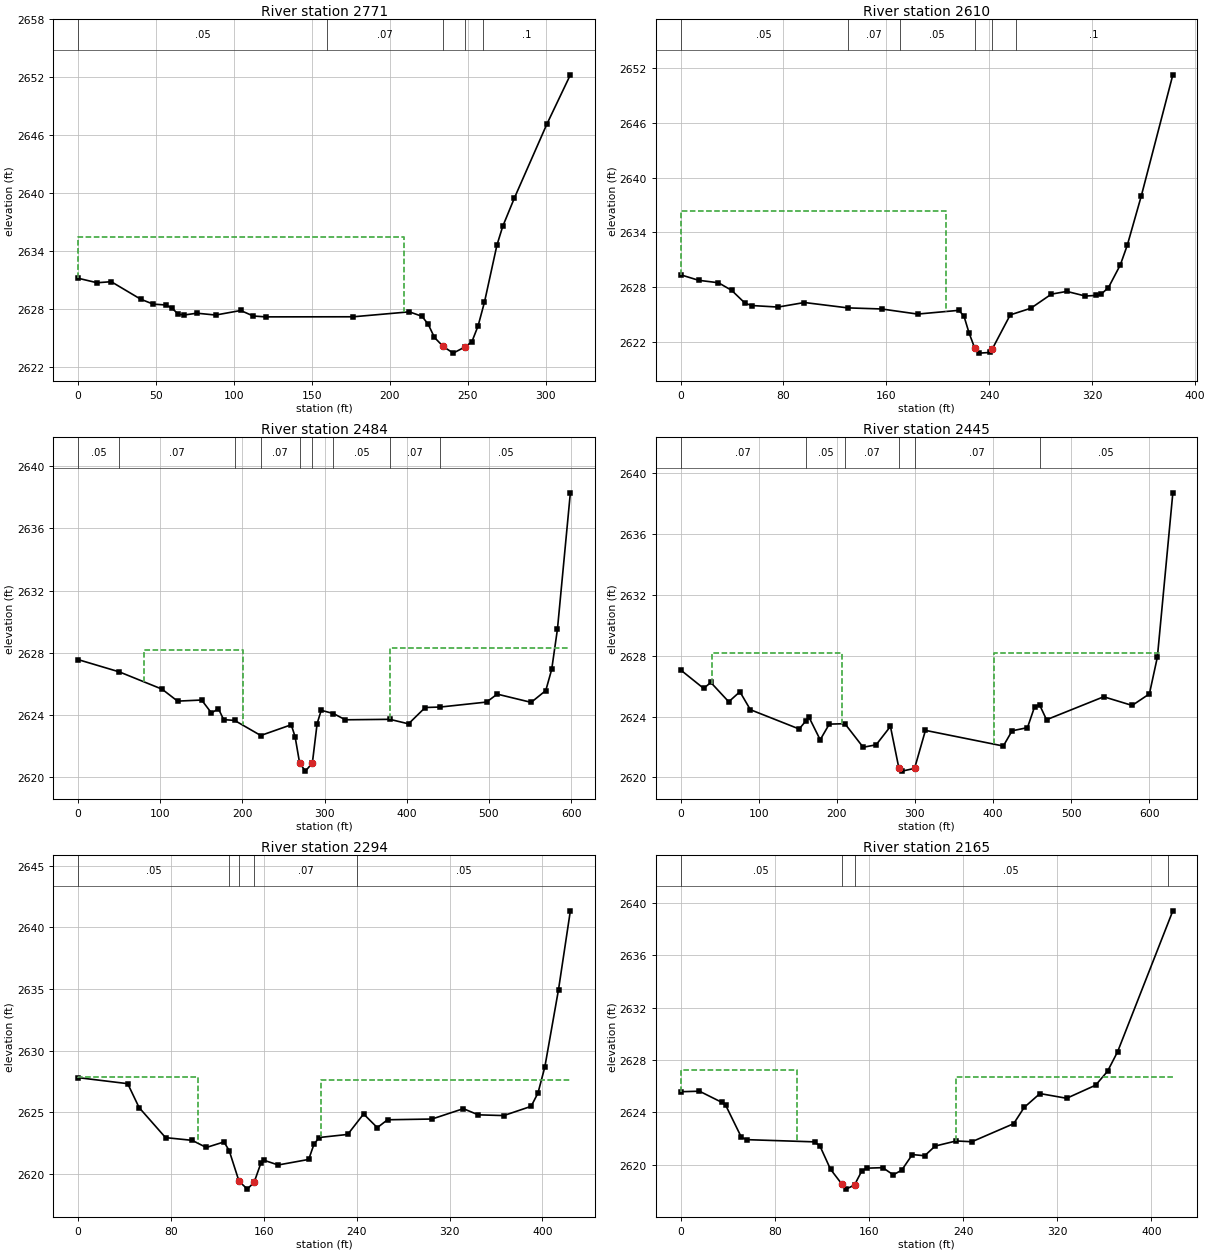
Type RM Length L Ch R = 1 ,2771    ,161.9,160.8,160.2
XS GIS Cut Line= 2
2309066.70827861530073.0463050752309044.93814113530388.240034709
#Sta/Elev= 30
       0 2631.23    12.2 2630.76    21.3 2630.87    40.2 2629.06    48.2 2628.55
    56.3 2628.46    60.3 2628.14    64.3  2627.5    68.3 2627.43    76.3 2627.61
    88.3 2627.42   104.4 2627.89   112.4 2627.32   120.4 2627.23   176.6 2627.24
   212.6 2627.75   220.7 2627.29   224.7 2626.46   228.7  2625.1   234.3 2624.17
   240.7 2623.48  248.382624.126   252.7 2624.65   256.7  2626.3   260.8 2628.76
   268.8 2634.66   272.5 2636.59     280 2639.53   300.8 2647.16   315.9 2652.27
#Mann= 5 ,-1,0
       0     .05       0     160     .07       0   234.3    .045       0
  248.38     .07       0     260      .1       0
#XS Ineff= 2 , 0
           209.3 2635.45
Permanent Ineff=
       F       F
Bank Sta=234.3,248.38
XS Rating Curve= 0 ,0
Exp/Cntr(USF)=0,0
Exp/Cntr=0.3,0.1

Type RM Length L Ch R = 1 ,2610    ,114.1,125.5,130.5
XS GIS Cut Line= 4
2308984.03280863530102.2295508292308889.50024599530219.311243263
2308890.03692721530374.6250832282308942.12908009 530431.22365457
#Sta/Elev= 30
       0 2629.34    14.1 2628.73    29.5 2628.46    39.8 2627.62    50.1 2626.22
    55.2 2625.96    75.8 2625.79    96.3 2626.29     130  2625.7   156.3 2625.58
   184.3 2625.02   216.3 2625.43   220.3 2624.81   224.3 2622.94   228.72621.278
   232.3 2620.73   240.3  2620.8  242.372621.193   256.3 2624.93   272.3 2625.66
   288.3 2627.21   300.3 2627.51   314.7    2627   323.3 2627.07   326.7 2627.18
   332.6 2627.92   341.9 2630.43   347.3 2632.59   358.2 2638.01   382.7  2651.3
#Mann= 6 ,-1,0
       0     .05       0     130     .07       0  170.48     .05       0
   228.7    .045       0  242.37     .05       0  260.48      .1       0
#XS Ineff= 2 , 0
          205.98  2636.3
Permanent Ineff=
       F       F
Bank Sta=228.7,242.37
XS Rating Curve= 0 ,0
Exp/Cntr(USF)=0,0
Exp/Cntr=0.3,0.1

Type RM Length L Ch R = 1 ,2484    ,38.3,39.2,39.9
XS GIS Cut Line= 4
 2308934.2236806530084.135726998 2308725.8093196530363.079155995
2308668.15939474530435.6132576842308742.87885118530574.944943321
#Sta/Elev= 30
       0 2627.56    50.2 2626.77   102.2 2625.66   121.1 2624.89   150.4 2624.96
   162.3 2624.13   170.8  2624.4   177.2  2623.7   190.5 2623.65   222.3 2622.68
   259.4 2623.37   264.1  2622.6  269.572620.919   276.6 2620.39   285.1 2620.91
   290.9 2623.45   295.9  2624.3   310.8 2624.09   325.2 2623.69   379.3 2623.72
   402.1 2623.43   422.4 2624.48   440.8 2624.51   497.1 2624.83     510 2625.34
   551.3 2624.81   569.1 2625.57   576.3 2626.93   583.3 2629.52     599 2638.28
#Mann= 9 ,-1,0
       0     .05       0    50.2     .07       0   190.5     .05       0
   222.3     .07       0  269.57    .045       0   285.1     .07       0
   310.8     .05       0   379.3     .07       0   440.8     .05       0
#XS Ineff= 2 ,-1
   80.19  200.972628.197  379.71   597.1  2628.3
Permanent Ineff=
       F       F
Bank Sta=269.57,285.1
XS Rating Curve= 0 ,0
Exp/Cntr(USF)=0,0
Exp/Cntr=0.3,0.1

Type RM Length L Ch R = 1 ,2445    ,172,151.3,140.1
XS GIS Cut Line= 4
2308902.70430764530065.3944782092308695.87991494530344.187062436
2308639.95950077530416.0949595212308736.02943517530582.297136618
#Sta/Elev= 30
       0 2627.07    29.6 2625.85    38.8 2626.24    61.7 2624.97      76 2625.63
    89.4 2624.45   151.9 2623.18   160.4 2623.71   164.6 2623.94   178.8 2622.47
   190.4  2623.5   210.4 2623.53   233.8 2621.98   250.4 2622.14   268.7 2623.35
   279.5 2620.61   283.6 2620.41   299.6 2620.59   313.5 2623.09   413.2 2622.06
   424.4 2623.06   444.1 2623.27   453.3 2624.65   459.7 2624.76   468.5 2623.79
   541.7  2625.3   578.1 2624.73   600.2 2625.49   610.4 2627.91   630.2 2638.71
#Mann= 6 ,-1,0
       0     .07       0   160.4     .05       0   210.4     .07       0
   279.5    .045       0   299.6     .07       0   459.7     .05       0
#XS Ineff= 2 ,-1
   40.58  206.28 2628.19  401.29  616.59 2628.19
Permanent Ineff=
       F       F
Bank Sta=279.5,299.6
XS Rating Curve= 0 ,0
Exp/Cntr(USF)=0,0
Exp/Cntr=0.3,0.1

Type RM Length L Ch R = 1 ,2294    ,128.2,128.6,129
XS GIS Cut Line= 2
2308528.16507596530219.079320251 2308732.5940288530590.612482972
#Sta/Elev= 30
       0  2627.8    42.8 2627.31    52.6 2625.37    75.4 2622.93    98.3 2622.71
   110.5 2622.13   125.7 2622.58   130.2 2621.88  138.692619.385   145.9 2618.75
   151.8 2619.33   157.6 2620.88   160.6 2621.08   172.4 2620.71   198.7 2621.16
   203.3 2622.41   207.8 2622.94   232.3 2623.19     246 2624.85   257.8 2623.74
   266.6 2624.38   304.9 2624.44   331.9 2625.28   344.8 2624.78   366.7 2624.72
   390.3 2625.47   396.2 2626.55   402.1 2628.66   413.9 2634.95   424.1 2641.34
#Mann= 5 ,-1,0
       0     .05       0     130     .07       0  138.69    .045       0
   151.8     .07       0     240     .05       0
#XS Ineff= 2 , 0
          103.06 2627.82  209.34         2627.61
Permanent Ineff=
       F       F
Bank Sta=138.69,151.8
XS Rating Curve= 0 ,0
Exp/Cntr(USF)=0,0
Exp/Cntr=0.3,0.1

Type RM Length L Ch R = 1 ,2165    ,167.6,172.4,172.5
XS GIS Cut Line= 3
2308423.50776034530278.6600708552308560.75427925530560.725330406
2308618.49246996530647.805880335
#Sta/Elev= 30
       0 2625.57    16.1 2625.61    35.3 2624.75    38.4 2624.53    51.7 2622.09
    56.2 2621.91     114 2621.74   118.5 2621.41   127.4 2619.65     137 2618.52
   140.7 2618.13   147.8 2618.45     154 2619.52     158 2619.73   171.8 2619.77
   180.7 2619.22   187.9 2619.58   196.9 2620.77   207.4 2620.68   216.3 2621.42
   234.1 2621.81   247.5 2621.75     283 2623.13   291.9 2624.37   305.3 2625.43
     328 2625.07   352.6 2626.07   362.7 2627.13   371.3 2628.63   418.2 2639.39
#Mann= 4 ,-1,0
       0     .05       0     137    .045       0   147.8     .05       0
  413.68      .1       0
#XS Ineff= 2 , 0
           99.03 2627.22   234.3         2626.69
Permanent Ineff=
       F       F
Bank Sta=137,147.8
XS Rating Curve= 0 ,0
Exp/Cntr(USF)=0,0
Exp/Cntr=0.3,0.1