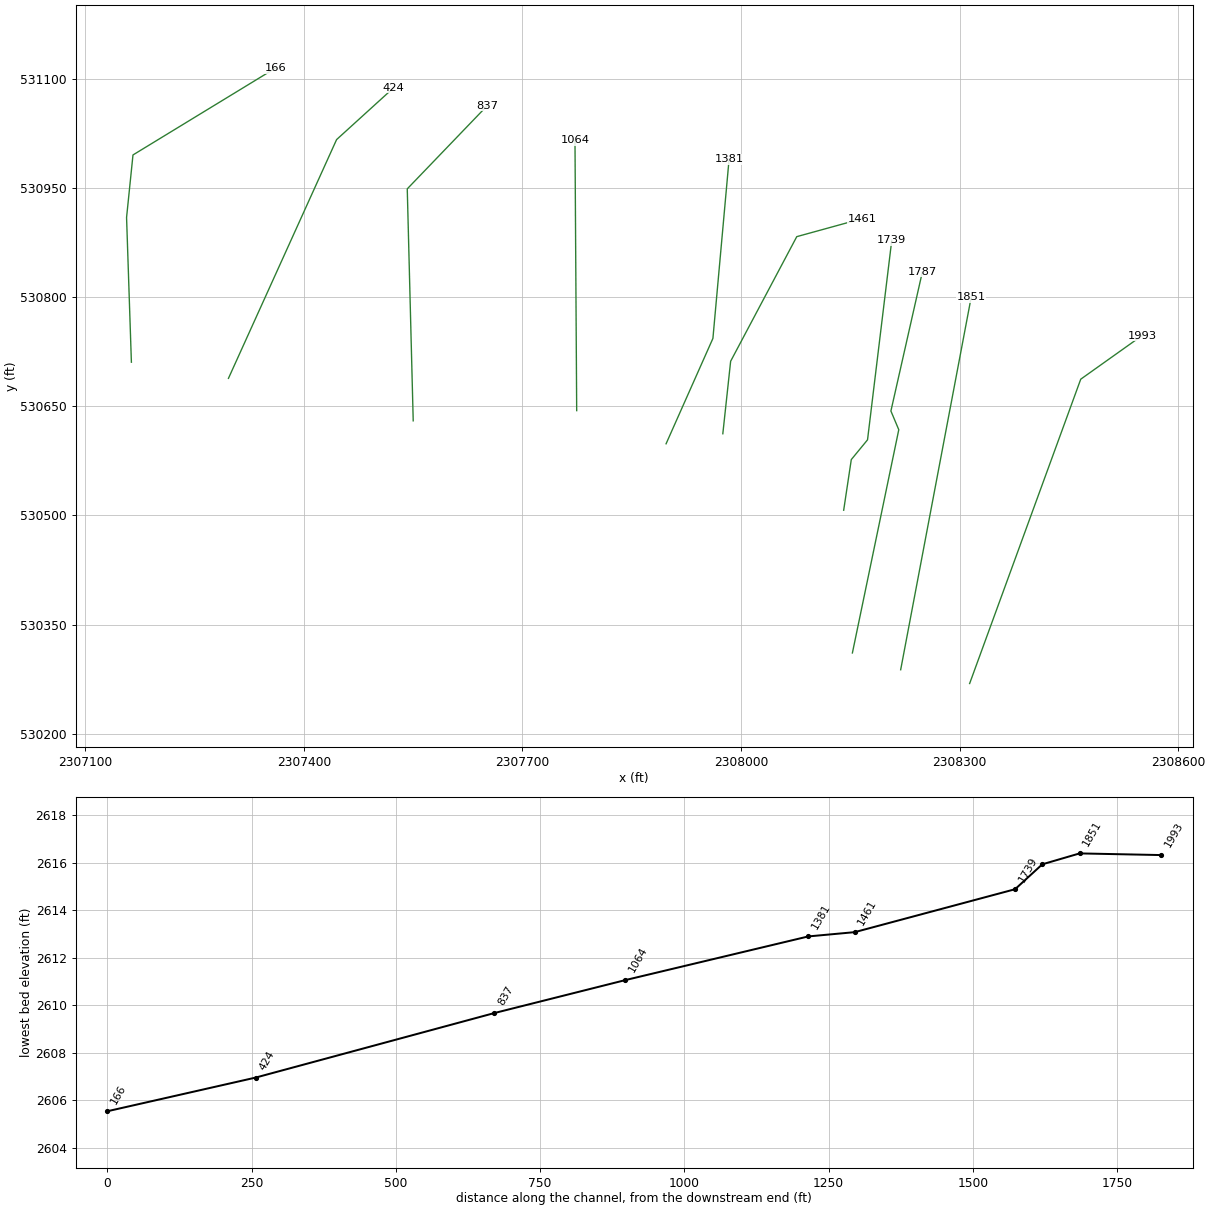
HEC-RAS study DNCNRN.prj: DNCNRN

--- DNCNRN.g01 (geometry) --- (continued)

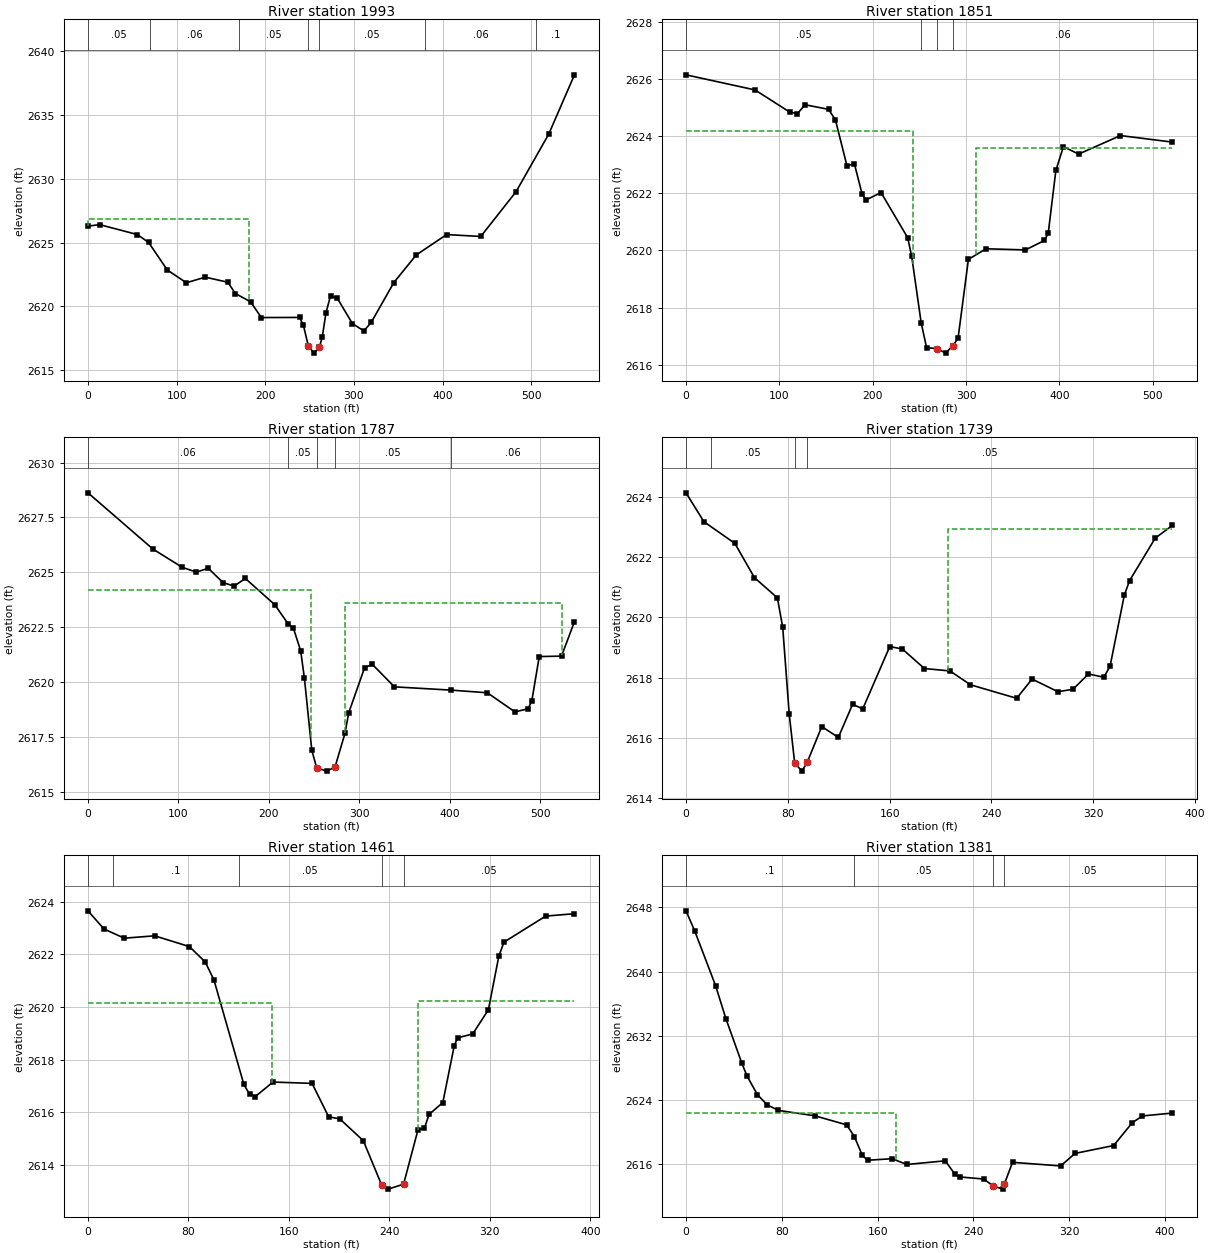
Type RM Length L Ch R = 1 ,1993    ,139.1,141.4,143.6
XS GIS Cut Line= 3
2308313.75117173530268.8831046072308466.24730386530687.458694844
2308550.38310089 530747.40545023
#Sta/Elev= 30
       0 2626.29    13.1 2626.41    55.7 2625.63    68.4 2625.01    89.5 2622.85
     111 2621.85   132.3 2622.29   157.8 2621.89   166.3    2621   183.4 2620.36
   195.6 2619.12   238.7 2619.13     243 2618.52   248.6 2616.89   254.9 2616.33
   261.1 2616.79   264.3  2617.6   268.5  2619.5   273.6 2620.82   281.3 2620.63
   298.3 2618.65   311.2 2618.07   319.6 2618.75   345.1 2621.87   370.3 2624.03
   404.6 2625.63   443.1 2625.48   482.9 2628.99   519.8 2633.51   548.8 2638.16
#Mann= 7 ,-1,0
       0     .05       0      70     .06       0     170     .05       0
   248.6    .045       0   261.1     .05       0     380     .06       0
  505.49      .1       0
#XS Ineff= 2 , 0
          181.64 2626.87
Permanent Ineff=
       F       F
Bank Sta=248.6,261.1
XS Rating Curve= 0 ,0
Exp/Cntr(USF)=0,0
Exp/Cntr=0.5,0.3

Type RM Length L Ch R = 1 ,1851    ,65.4,64.7,64.6
XS GIS Cut Line= 2
2308219.09840007 530287.813658942308315.85456666530799.990323375
#Sta/Elev= 30
       0 2626.16      74 2625.63   111.3 2624.85   119.4  2624.8   127.6 2625.11
   152.7 2624.95   160.1 2624.58   172.4 2622.98   180.5 2623.03   188.6 2621.99
   192.7 2621.77     209 2622.03   237.5 2620.45   241.8  2619.8     252 2617.46
   257.8 2616.59   269.2 2616.56   278.2  2616.4   285.9 2616.66   291.5 2616.92
   302.6 2619.69   321.6 2620.06   363.7 2620.02     384 2620.35   388.1  2620.6
   396.3 2622.81   404.4 2623.64   420.7 2623.38   465.5 2624.03   521.2  2623.8
#Mann= 4 ,-1,0
       0     .05       0     252     .06       0   269.2    .045       0
   285.9     .06       0
#XS Ineff= 2 , 0
             243  2624.2     311          2623.6
Permanent Ineff=
       F       F
Bank Sta=269.2,285.9
XS Rating Curve= 0 ,0
Exp/Cntr(USF)=0,0
Exp/Cntr=0.5,0.3

Type RM Length L Ch R = 1 ,1787    ,55.7,47.2,43
XS GIS Cut Line= 4
2308152.84145991530310.9510031242308216.50220688530617.969925619
2308205.69381727530643.6749626212308248.90400435530835.152716188
#Sta/Elev= 30
       0 2628.62    71.7 2626.06   104.4 2625.22   119.7 2625.01     133 2625.18
   149.3 2624.53   161.6 2624.37   173.9 2624.72   206.5 2623.52   221.2 2622.65
     227 2622.46   235.1 2621.42   239.2 2620.18   247.4 2616.89   252.8 2616.09
   263.7 2615.94  272.992616.119   284.1 2617.67   288.2  2618.6   305.8 2620.66
   314.4  2620.8   338.7 2619.78   401.6 2619.63   441.4 2619.51   471.9 2618.64
   486.5 2618.78   490.6 2619.15   498.8 2621.16   523.4 2621.18   537.7 2622.75
#Mann= 5 ,-1,0
       0     .06       0   221.2     .05       0   252.8    .045       0
  272.99     .05       0   401.6     .06       0
#XS Ineff= 2 ,-1
       0     246  2624.2     284   523.9  2623.6
Permanent Ineff=
       F       F
Bank Sta=252.8,272.99
XS Rating Curve= 0 ,0
Exp/Cntr(USF)=0,0
Exp/Cntr=0.5,0.3

Type RM Length L Ch R = 1 ,1739    ,278.9,277.9,286.5
XS GIS Cut Line= 4
2308140.87695702 530507.242972142308151.32407272530576.890410118
2308173.61125287530604.0529109292308206.89158464530878.652561116
#Sta/Elev= 30
       0 2624.14    14.1 2623.18    38.4 2622.46    53.8 2621.32    71.8 2620.65
      76 2619.67    81.1 2616.79    85.4 2615.16    91.1 2614.89    95.2 2615.18
   106.7 2616.37   119.7 2616.01   130.9 2617.11   138.9 2616.96   160.1 2619.03
     170 2618.95   187.3  2618.3   207.4 2618.22   223.5 2617.76   259.8 2617.31
   271.9 2617.95   292.2 2617.53   304.1 2617.61   316.2 2618.12   328.3 2618.01
   333.2 2618.38   344.4 2620.74   348.5 2621.22   368.6 2622.63   382.2 2623.06
#Mann= 4 ,-1,0
       0     .06       0      20     .05       0    85.4    .045       0
    95.2     .05       0
#XS Ineff= 2 , 0
                          206.12         2622.93
Permanent Ineff=
       F       F
Bank Sta=85.4,95.2
XS Rating Curve= 0 ,0
Exp/Cntr(USF)=0,0
Exp/Cntr=0.3,0.1

Type RM Length L Ch R = 1 ,1461    ,77.9,80.4,88.8
XS GIS Cut Line= 4
2307974.99847734530612.4116856292307985.73517539530712.132062715
2308076.49207946530883.4883375072308166.25988841 530908.25187101
#Sta/Elev= 30
       0 2623.66    12.7 2622.97    28.9 2622.62    53.1 2622.71    80.7  2622.3
    93.3 2621.72   100.3 2621.03   124.1 2617.06   128.6 2616.69   133.2  2616.6
   147.3 2617.15   178.4  2617.1   191.6 2615.83   200.5 2615.75   219.2 2614.92
   233.7 2613.25     239 2613.08  251.252613.268   262.7 2615.33   267.9  2615.4
   271.5 2615.92   282.5 2616.37   291.6 2618.53   294.2 2618.83   306.3 2618.98
   318.8  2619.9   327.1 2621.94   331.2 2622.47   364.4 2623.46   387.3 2623.55
#Mann= 5 ,-1,0
       0     .05       0      20      .1       0   120.3     .05       0
   233.7    .045       0  251.25     .05       0
#XS Ineff= 2 , 0
          146.86 2620.15   262.8         2620.24
Permanent Ineff=
       F       F
Bank Sta=233.7,251.25
XS Rating Curve= 0 ,0
Exp/Cntr(USF)=0,0
Exp/Cntr=0.3,0.1

Type RM Length L Ch R = 1 ,1381    ,315.6,316.9,309.9
XS GIS Cut Line= 3
2307897.13318015530598.6331811812307961.40358066530743.533720515
2307983.60608266 530990.09834793
#Sta/Elev= 30
       0 2647.58     7.2 2645.11    24.7 2638.26    33.4 2634.11    46.5 2628.64
    50.9 2627.01    59.7 2624.66    67.9 2623.39    77.2 2622.71   107.8 2622.03
   134.1 2620.91   140.6 2619.45   147.2 2617.11   151.6  2616.5   172.2 2616.69
   184.3 2615.97   216.4 2616.43   224.4 2614.78   228.4 2614.42   248.5 2614.16
   256.6 2613.28   264.6  2612.9   265.7  2613.5   272.6 2616.24   312.8 2615.79
   324.8 2617.35     357 2618.33   372.6 2621.18   381.1 2622.02   406.1 2622.38
#Mann= 4 ,-1,0
       0      .1       0   140.6     .05       0   256.6    .045       0
   265.7     .05       0
#XS Ineff= 2 , 0
       0  175.52 2622.33               0
Permanent Ineff=
       F       F
Bank Sta=256.6,265.7
XS Rating Curve= 0 ,0
Exp/Cntr(USF)=0,0
Exp/Cntr=0.3,0.1

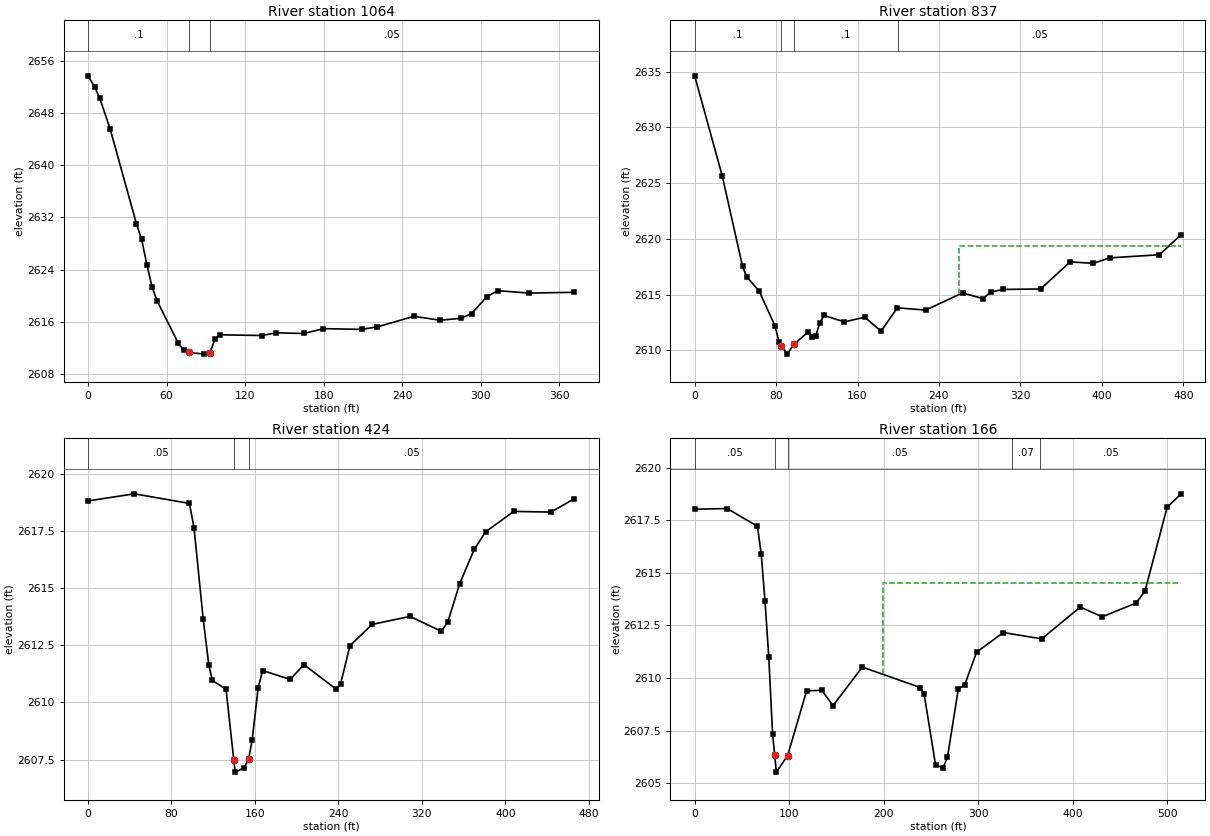
Type RM Length L Ch R = 1 ,1064    ,226.8,227.1,227.5
XS GIS Cut Line= 2
2307774.43514281530644.2067379072307772.09803734531015.806508134
#Sta/Elev= 30
       0 2653.68       5 2652.01       9 2650.25      17  2645.5      37 2631.03
      41 2628.62      45 2624.75      49  2621.3      53 2619.13      69 2612.73
      73 2611.67      77 2611.31      89 2611.06   93.232611.306      97 2613.39
     101 2614.02     133 2613.91   143.6 2614.32     165 2614.22   179.8 2614.96
     209 2614.85     221 2615.23     249 2616.85     269 2616.25     285 2616.55
     293 2617.26   304.6 2619.83     313 2620.78   336.8 2620.41   371.6 2620.53
#Mann= 3 ,-1,0
       0      .1       0      77    .045       0   93.23     .05       0
Bank Sta=77,93.23
XS Rating Curve= 0 ,0
Exp/Cntr(USF)=0,0
Exp/Cntr=0.3,0.1

Type RM Length L Ch R = 1 ,837     ,415.2,413.6,405.8
XS GIS Cut Line= 3
2307550.07301739530630.1841050682307541.89314824 530949.19900215
2307651.73710548531063.717170333
#Sta/Elev= 30
       0 2634.62      27 2625.68      47 2617.55      51  2616.6    63.3 2615.34
      79 2612.18      83 2610.72   84.892610.437      91 2609.67   97.252610.536
     111 2611.61     115 2611.17     119 2611.34     123 2612.49     127 2613.14
     147 2612.56     167 2612.98   183.1 2611.73   199.1 2613.82     227 2613.62
   263.1 2615.16   283.1 2614.65   291.1 2615.24   303.1 2615.47   339.8 2615.51
   368.8 2617.94   391.4 2617.81   407.8  2618.3   456.5 2618.58   477.8 2620.38
#Mann= 4 ,-1,0
       0      .1       0   84.89    .045       0   97.25      .1       0
     200     .05       0
#XS Ineff= 2 , 0
                          260.06          2619.4
Permanent Ineff=
       F       F
Bank Sta=84.89,97.25
XS Rating Curve= 0 ,0
Exp/Cntr(USF)=0,0
Exp/Cntr=0.3,0.1

Type RM Length L Ch R = 1 ,424     ,249.7,257.1,261
XS GIS Cut Line= 3
2307296.49707356530688.611741896 2307444.9032711531016.975060871
2307523.19630445531088.256777801
#Sta/Elev= 30
       0 2618.83    44.5 2619.14    97.2 2618.72   101.6 2617.66   110.4 2613.66
   115.8 2611.65   119.1 2610.97   132.3 2610.58  139.692607.497   141.1 2606.95
   149.9 2607.15     154 2607.53   157.4 2608.37     163 2610.62   167.4  2611.4
   193.8 2611.01   206.9 2611.66   237.7 2610.59   242.1 2610.82   251.1 2612.49
   272.3 2613.42   308.6 2613.77   338.6 2613.12   344.8 2613.52   356.2  2615.2
   370.2 2616.71     381 2617.47     408 2618.37   443.8 2618.34   466.2 2618.93
#Mann= 3 ,-1,0
       0     .05       0  139.69    .045       0     154     .05       0
Bank Sta=139.69,154
XS Rating Curve= 0 ,0
Exp/Cntr(USF)=0,0
Exp/Cntr=0.3,0.1

Type RM Length L Ch R = 1 ,166     ,31,31,31
XS GIS Cut Line= 4
2307163.28206159530710.8142438912307156.64991327530909.878425629
2307165.45688779530995.853957597 2307360.8295709531115.189000436
#Sta/Elev= 30
       0 2618.02    34.4 2618.05    66.4 2617.21    70.4 2615.89    74.4 2613.66
    78.4    2611    82.4 2607.35    84.72606.323    86.4 2605.53    98.3 2606.31
   118.4 2609.39   134.4 2609.42   146.4 2608.69   177.3 2610.52   238.7 2609.55
   242.7 2609.24   254.8 2605.87   262.8 2605.74   267.4 2606.24   278.9 2609.49
   285.6 2609.67   298.2 2611.23   326.5 2612.16   367.1 2611.86   407.8 2613.37
   431.1 2612.91   466.9 2613.56   476.3 2614.13   499.7 2618.11   514.5 2618.75
#Mann= 5 ,-1,0
       0     .05       0    84.7    .045       0    98.3     .05       0
   335.6     .07       0   365.6     .05       0
#XS Ineff= 2 , 0
                          199.03         2614.51
Permanent Ineff=
       F       F
Bank Sta=84.7,98.3
XS Rating Curve= 0 ,0
Exp/Cntr(USF)=0,0
Exp/Cntr=0.3,0.1
LCMann Table=0

Chan Stop Cuts=-1
Use User Specified Reach Order=0
Composite Channel Slope=5